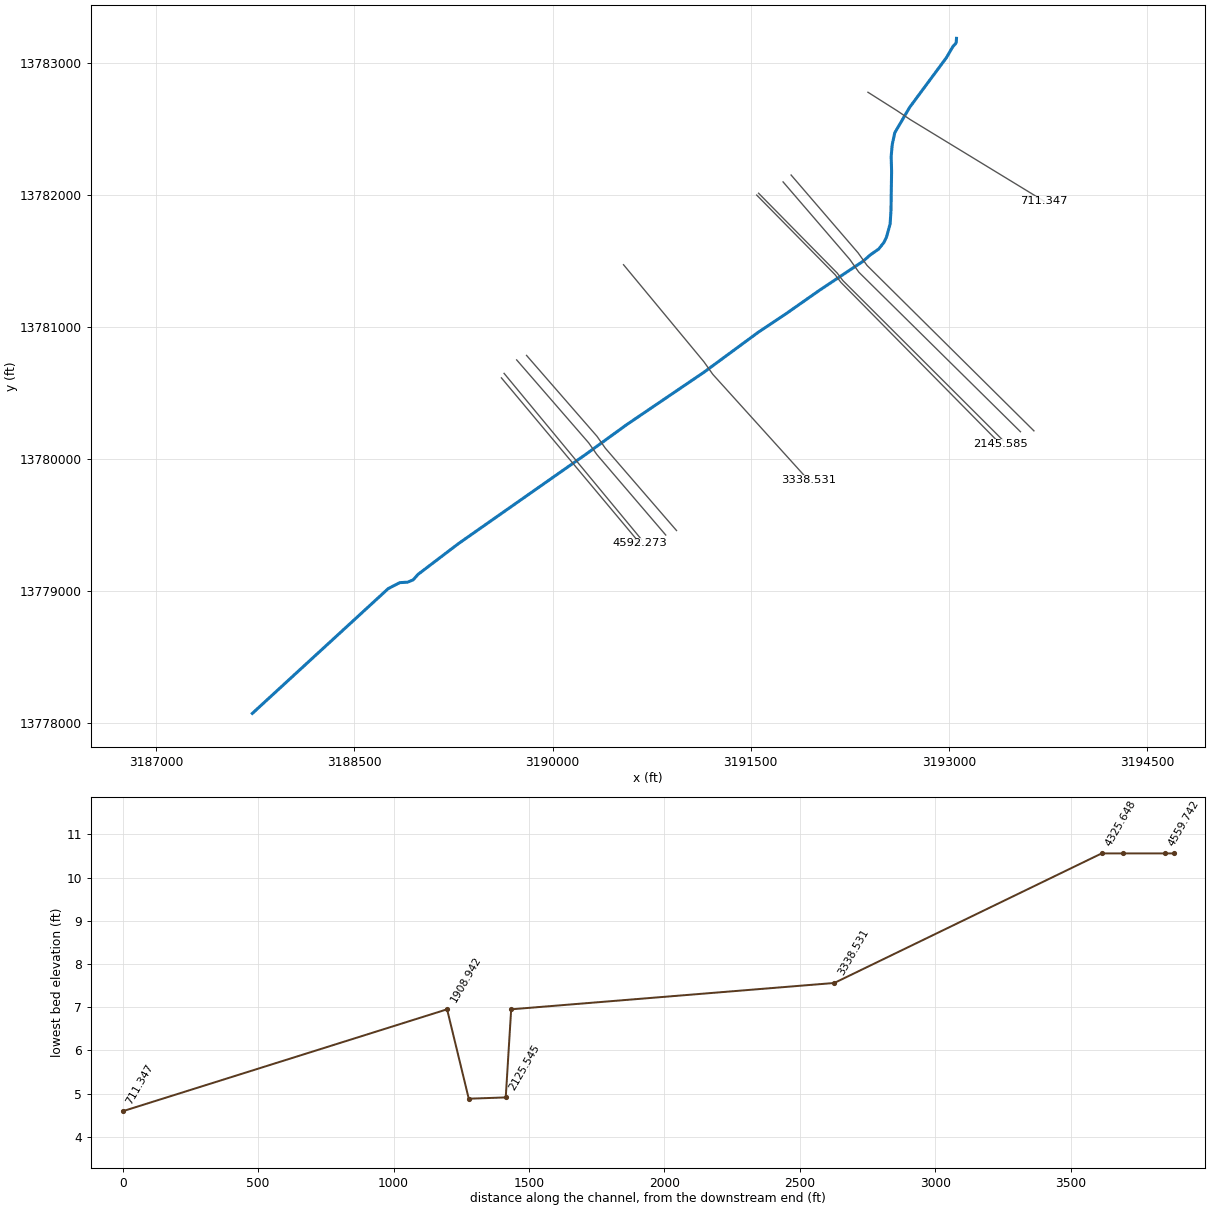
--- B104_05_00.prj (project) ---

Proj Title=B104-05-00
Current Plan=p01
Default Exp/Contr=.3,.1
English Units
Geom File=g02
Geom File=g01
Flow File=f02
Flow File=f01
Plan File=p02
Plan File=p01
Y Axis Title=Elevation
X Axis Title(PF)=Main Channel Distance
X Axis Title(XS)=Station
BEGIN DESCRIPTION:
Armand Bayou
Horsepen Bayou Tributary 5.44
HCFCD Unit B104-05-00
Flood Hazard Model
10, 2, 1, 0.2% Event
Filename B104_05_00.prj
Prepared by: Christopher Moss Date: 6/15/2004
Reviewd by:		Date:
Status FINAL
END DESCRIPTION:
DSS Export Rating Curves= 0
DSS Export Rating Curve Sorted= 0
DSS Export Volume Flow Curves= 0
DXF OffsetX= 0
DXF OffsetY= 0
DXF ScaleX= 1
DXF ScaleY= 10

--- B104_05_00.p01 (plan) ---

Plan Title=FEMA Effective June 2007
Version=Version 3.0.1  Mar 2001
Short Identifier=FEMAeff0607
Geom File=g01
Flow File=f01
Subcritical Flow
K Sum by GR= 0
Std Step Tol= 0.01
Critical Tol= 0.01
Num of Std Step Trials= 20
Max Error Tol= 0.3
Flow Tol Ratio= 0.001
Split Flow NTrial= 30
Split Flow Tol= 0.02
Split Flow Ratio= 0.02
Log Output Level= 0
Friction Slope Method= 0
Unsteady Friction Slope Method= 2
Secant Critical Depth
Global Vel Dist= 0 , 0 , 0
Global Log Level= 0
CheckData=True
Encroach Param=-1 ,0,0, 0
Computation Interval=1HOUR
Output Interval=1HOUR
Run HTab= 0
Run UNet= 0
Run PostProcess= 0
UNET Theta= 1
UNET ZTol= 0.02
UNET ZSATol= 0.1
UNET MxIter= 20
UNET MaxInSteps= 20
UNET DtIC= 0
UNET DtMin= 0
UNET MaxCRTS= 20
UNET WFStab= 2
UNET SFStab= 1
UNET WFX= 1
UNET SFX= 1
UNET Convert EG Bridges=-1
UNET Use Existing IB Tables=-1
Instantaneous Interval=1HOUR
Write IC File= 0
Write Velocity= 0
Write Detailed= 0

--- B104_05_00.p02 (plan) ---

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Plan Title=Floodway
Short Identifier=Floodway0607
Geom File=g02
Flow File=f02
Encroach Param=-1 ,0,0, 2
Encroach River=B104-05-00
Encroach Reach=Main
Encroach Node=4592.273
       1 4945.17 5054.83
Encroach Node=4559.742
       1 4945.17 5054.83
Encroach Node=4482.7
       1 4945.17 5054.83
Encroach Node=4405.659
       1 4945.17 5054.83
Encroach Node=4325.648
       1 4945.17 5054.83
Encroach Node=3338.531
       1 4941.95 5058.05
Encroach Node=2145.585
       1 4943.27 5063.25
Encroach Node=2125.545
       1 4943.27 5063.25
Encroach Node=2057.3
       1 4943.27 5063.25
Encroach Node=1989.013
       1 4943.27 5063.25
Encroach Node=1908.942
       1 4943.27 5063.25
Encroach Node=711.347
       1 4940.95 5059.05
Encroach Reach=B104-05-00_0007
Encroach Node=4592.273
       1 4945.17 5054.83
Encroach Node=4559.742
       1 4945.17 5054.83
Encroach Node=4482.7
       1 4945.17 5054.83
Encroach Node=4405.659
       1 4945.17 5054.83
Encroach Node=4325.648
       1 4945.17 5054.83
Encroach Node=3338.531
       1 4941.95 5058.05
Encroach Node=2145.585
       1 4943.27 5063.25
Encroach Node=2125.545
       1 4943.27 5063.25
Encroach Node=2057.3
       1 4943.27 5063.25
Encroach Node=1989.013
       1 4943.27 5063.25
Encroach Node=1908.942
       1 4943.27 5063.25
Encroach Node=711.347
       1 4940.95 5059.05
IC Time=0

--- B104_05_00.f01 (steady flow) ---

Flow Title=FEMA Effective June 2007
Version=Version 3.0.1  Mar 2001
Number of Profiles= 4
Profile Names=10PCT_10yr, 2PCT_50yr, 1PCT_100yr, 0.2PCT_500yr
River Rch & RM=B104-05-00,B104-05-00_0007            ,4592.273
     819    1230    1443    2066
River Rch & RM=B104-05-00,B104-05-00_0007            ,4325.648
     929    1386    1623    2312
River Rch & RM=B104-05-00,B104-05-00_0007            ,3338.531
    1081    1602    1871    2647
River Rch & RM=B104-05-00,B104-05-00_0007            ,2145.585
    1115    1648    1925    2719
River Rch & RM=B104-05-00,B104-05-00_0007            ,1908.942
    1299    1906    2220    3115
Boundary for River Rch & Prof#=B104-05-00,B104-05-00_0007            , 1
Up Type= 0
Dn Type= 3
Dn Slope=.0015
DSS Import GetInterval= 0
DSS Import GetPeak= 0
DSS Import FillOption= 0

--- B104_05_00.f02 (steady flow) ---

Flow Title=Floodway
Version=Version 3.0.1  Mar 2001
Number of Profiles= 2
Profile Names=1PCT_100yr, 1PCTFloodway_100yrFW
River Rch & RM=B104-05-00,B104-05-00_0007            ,4592.273
    1443    1443
River Rch & RM=B104-05-00,B104-05-00_0007            ,4325.648
    1623    1623
River Rch & RM=B104-05-00,B104-05-00_0007            ,3338.531
    1871    1871
River Rch & RM=B104-05-00,B104-05-00_0007            ,2145.585
    1925    1925
River Rch & RM=B104-05-00,B104-05-00_0007            ,1908.942
    2220    2220
Boundary for River Rch & Prof#=B104-05-00,B104-05-00_0007            , 1
Up Type= 0
Dn Type= 3
Dn Slope=.0015
Boundary for River Rch & Prof#=B104-05-00,B104-05-00_0007            , 2
Up Type= 0
Dn Type= 3
Dn Slope=.0015
DSS Import GetInterval= 0
DSS Import GetPeak= 0
DSS Import FillOption= 0

--- B104_05_00.g01 (geometry) ---

Geom Title=B104-05-00 June 2007
Program Version=3.10

River Reach=B104-05-00      ,B104-05-00_0007
Reach XY= 30
     3187727.465    13778075.651     3188755.584    13779019.842
      3188843.01    13779065.303     3188902.459      13779068.8
     3188944.423    13779086.285      3188981.75       13779128.
        3189288.       13779361.      3190252.25       13780037.
      3190559.25       13780260.       3191144.5       13780657.
      3191556.25       13780960.      3191773.25       13781105.
       3192018.5       13781277.      3192350.25       13781498.
      3192404.75       13781546.        3192469.       13781591.
        3192509.       13781641.      3192528.25       13781682.
       3192555.5       13781780.        3192562.       13781880.
      3192566.75       13782181.       3192563.5       13782292.
       3192571.5       13782381.      3192590.75       13782471.
        3192703.       13782663.        3192982.       13783040.
      3193030.75       13783124.      3193050.75       13783145.
       3193056.5       13783157.        3193058.       13783186.

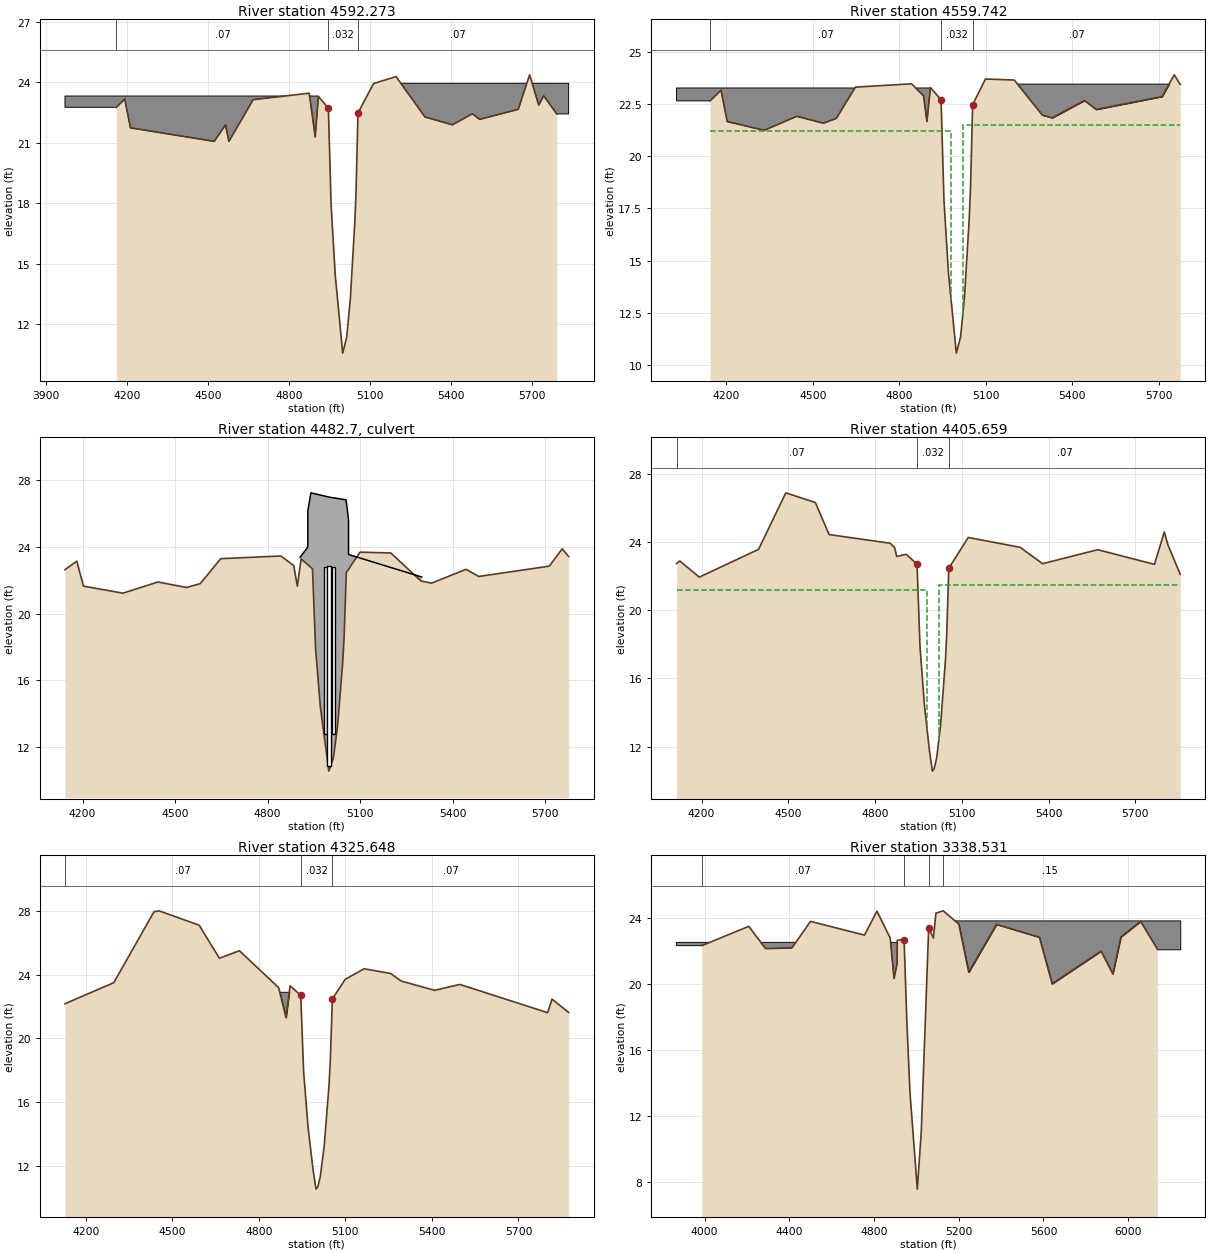
Type RM Length L Ch R = 1 ,4592.273,33.12,32.53,31.94
XS GIS Cut Line= 2
     3189612.747    13780615.602     3190659.709    13779364.686
#Sta/Elev= 30
 4159.92   22.75 4190.61   23.16 4212.01   21.73  4522.5   21.06 4564.01   21.88
 4576.67   21.06 4666.65   23.13 4874.28   23.45 4896.31   21.28 4908.27   23.29
 4945.17    22.7  4955.2   17.91  4970.6   14.43 4998.16   10.56 5012.94   11.34
 5026.63   13.28 5043.09   17.05 5047.46    18.5 5054.83   22.47 5112.52   23.93
  5195.9   24.27 5303.02   22.27 5404.82   21.88 5478.49   22.43 5505.63   22.15
 5648.63   22.65 5690.65   24.36 5724.44   22.86 5742.92   23.32 5791.15   22.42
#Mann= 3 ,-1 , 0
 4159.92     .07       0 4945.17    .032       0 5054.83     .07       0
#Block Obstruct= 2 ,-1
 3969.36 4908.08   23.31 5128.81  5835.2   23.94
Bank Sta=4945.17,5054.83
XS Rating Curve= 0
Exp/Cntr=0.5,0.3

Type RM Length L Ch R = 1 ,4559.742,157.65,154.08,150.74
XS GIS Cut Line= 2
     3189633.142    13780649.594     3190673.306     13779391.88
#Sta/Elev= 30
 4143.14   22.65 4181.52   23.16 4202.93   21.66 4331.12   21.24 4444.43   21.91
 4537.01   21.58 4581.55   21.81 4647.88   23.31 4842.99   23.47 4884.42   22.89
 4896.13   21.66 4908.27   23.29 4945.17    22.7  4955.2   17.91  4970.6   14.43
 4998.16   10.56 5012.94   11.34 5026.63   13.28 5043.09   17.05 5047.46    18.5
 5054.83   22.47 5099.25    23.7  5199.2   23.65 5296.52   21.97 5331.05   21.84
 5442.84   22.67 5483.62   22.24 5712.36   22.86 5754.42    23.9 5775.25   23.44
#Mann= 3 ,-1 , 0
 4143.14     .07       0 4945.17    .032       0 5054.83     .07       0
#XS Ineff= 2 , 0
       0    4980    21.2    5020       0    21.5
Permanent Ineff=
       F       F
#Block Obstruct= 2 ,-1
 4027.15 4909.54   23.27 5095.96 5767.14   23.48
Bank Sta=4945.17,5054.83
XS Rating Curve= 0
Exp/Cntr=0.5,0.3

Type RM Length L Ch R = 2 ,4482.7  ,,,
BEGIN DESCRIPTION:
Crescent Landing
END DESCRIPTION:
Bridge Culvert--1,0,-1,-1, 0
Deck Dist Width WeirC Skew NumUp NumDn MinLoCord MaxHiCord MaxSubmerge Is_Ogee
49,56,2.6,0, 9, 9, , , 0.95, 0, 0,0,,
    4905 4929.99    4930    4940    5000    5054    5062 5062.01    5299
    23.4      24   26.16   27.26      27   26.84   25.64   23.56   22.21
                                                                        
    4905 4929.99    4930    4940    5000    5054    5062 5062.01    5299
    23.4      24   26.16   27.26      27   26.84   25.64   23.56   22.21
                                                                        
Multiple Barrel Culv=2,10,10,56,0.012,0.2,1,10,1,12.79,12.79, 2,Culvert #1  , 0 ,49
    4986    4986    5014    5014
Culvert Bottom n=0.012
Culvert=2,12,12,56,0.012,0.2,1,10,1,10.87,4999,10.87,4999,Culvert #2  , 0 ,49
Culvert Bottom n=0.012
BC Design=,, 0 ,, 0 ,,,,,,
BC HTab HWMax=23.9

Type RM Length L Ch R = 1 ,4405.659,80.22,80.01,80.53
XS GIS Cut Line= 4
     3189728.321    13780751.571      3190273.53    13780123.582
      3190336.47    13780033.793     3190856.864    13779425.872
#Sta/Elev= 30
 4113.57   22.75 4124.81    22.9 4192.16   21.95 4397.04   23.58 4491.34    26.9
 4593.56   26.33 4640.93   24.45  4852.3   23.94 4867.41   23.69 4874.79   23.17
 4908.27   23.29 4945.17    22.7  4955.2   17.91  4970.6   14.43 4987.87   11.77
 4998.16   10.56 5004.24    10.7 5012.94   11.34 5026.63   13.28 5043.09   17.05
 5047.46    18.5 5054.83   22.47 5122.05   24.28 5301.65    23.7 5378.95   22.74
  5569.8   23.56 5765.93    22.7 5800.03    24.6  5812.5   23.85  5855.1   22.11
#Mann= 3 ,-1 , 0
 4113.57     .07       0 4945.17    .032       0 5054.83     .07       0
#XS Ineff= 2 , 0
       0    4980    21.2    5020       0    21.5
Permanent Ineff=
       F       F
Bank Sta=4945.17,5054.83
XS Rating Curve= 0
Exp/Cntr=0.5,0.3

Type RM Length L Ch R = 1 ,4325.648,988.12,987.12,988.05
XS GIS Cut Line= 4
     3189803.104    13780785.563     3190336.751    13780172.765
     3190399.603    13780083.102     3190938.446    13779459.864
#Sta/Elev= 30
 4127.89   22.17    4297   23.49 4436.49   27.93 4453.96   27.99  4593.2   27.09
 4663.15   25.02 4732.67   25.49 4868.57   23.18 4894.03   21.31 4908.27   23.29
 4945.17    22.7  4955.2   17.91  4970.6   14.43 4987.87   11.77 4998.16   10.56
 5004.24    10.7 5012.94   11.34 5026.63   13.28 5043.09   17.05 5047.46    18.5
 5054.83   22.47 5099.25    23.7 5164.55   24.36 5256.38   24.07 5293.82   23.59
 5409.15   23.01 5496.79   23.38 5801.17   21.61 5816.12   22.46 5873.86   21.63
#Mann= 3 ,-1 , 0
 4127.89     .07       0 4945.17    .032       0 5054.83     .07       0
#Block Obstruct= 1 ,-1
  4826.6 4920.47   22.92
Bank Sta=4945.17,5054.83
XS Rating Curve= 0
Exp/Cntr=0.3,0.1

Type RM Length L Ch R = 1 ,3338.531,1183.4,1192.95,1198.54
XS GIS Cut Line= 4
     3190537.337    13781472.208     3191146.291    13780736.926
      3191213.32    13780642.131     3191937.819    13779840.578
#Sta/Elev= 30
 3986.76   22.31 4208.65   23.48 4288.01   22.13 4411.91   22.17 4500.23   23.78
 4754.95   22.95 4813.73    24.4 4876.37   22.77 4894.41   20.32 4909.23   21.23
 4909.75   22.64 4941.95   22.68 4955.01   17.68  4969.9   13.38 5004.43    7.56
 5023.12   11.04 5058.05   23.38 5080.33   22.77 5092.24   24.28 5126.93   24.42
 5200.09   23.62 5247.32    20.7 5378.21    23.6 5580.78   22.82 5640.95      20
 5871.84   21.98  5927.5    20.6  5965.6   22.84 6058.69   23.78 6138.02   22.09
#Mann= 4 ,-1 , 0
 3986.76     .07       0 4941.95    .032       0 5058.05     .07       0
 5126.93     .15       0
#Block Obstruct= 2 ,-1
 3867.67 4927.64   22.51 5134.94 6245.76   23.84
Bank Sta=4941.95,5058.05
XS Rating Curve= 0
Exp/Cntr=0.3,0.1

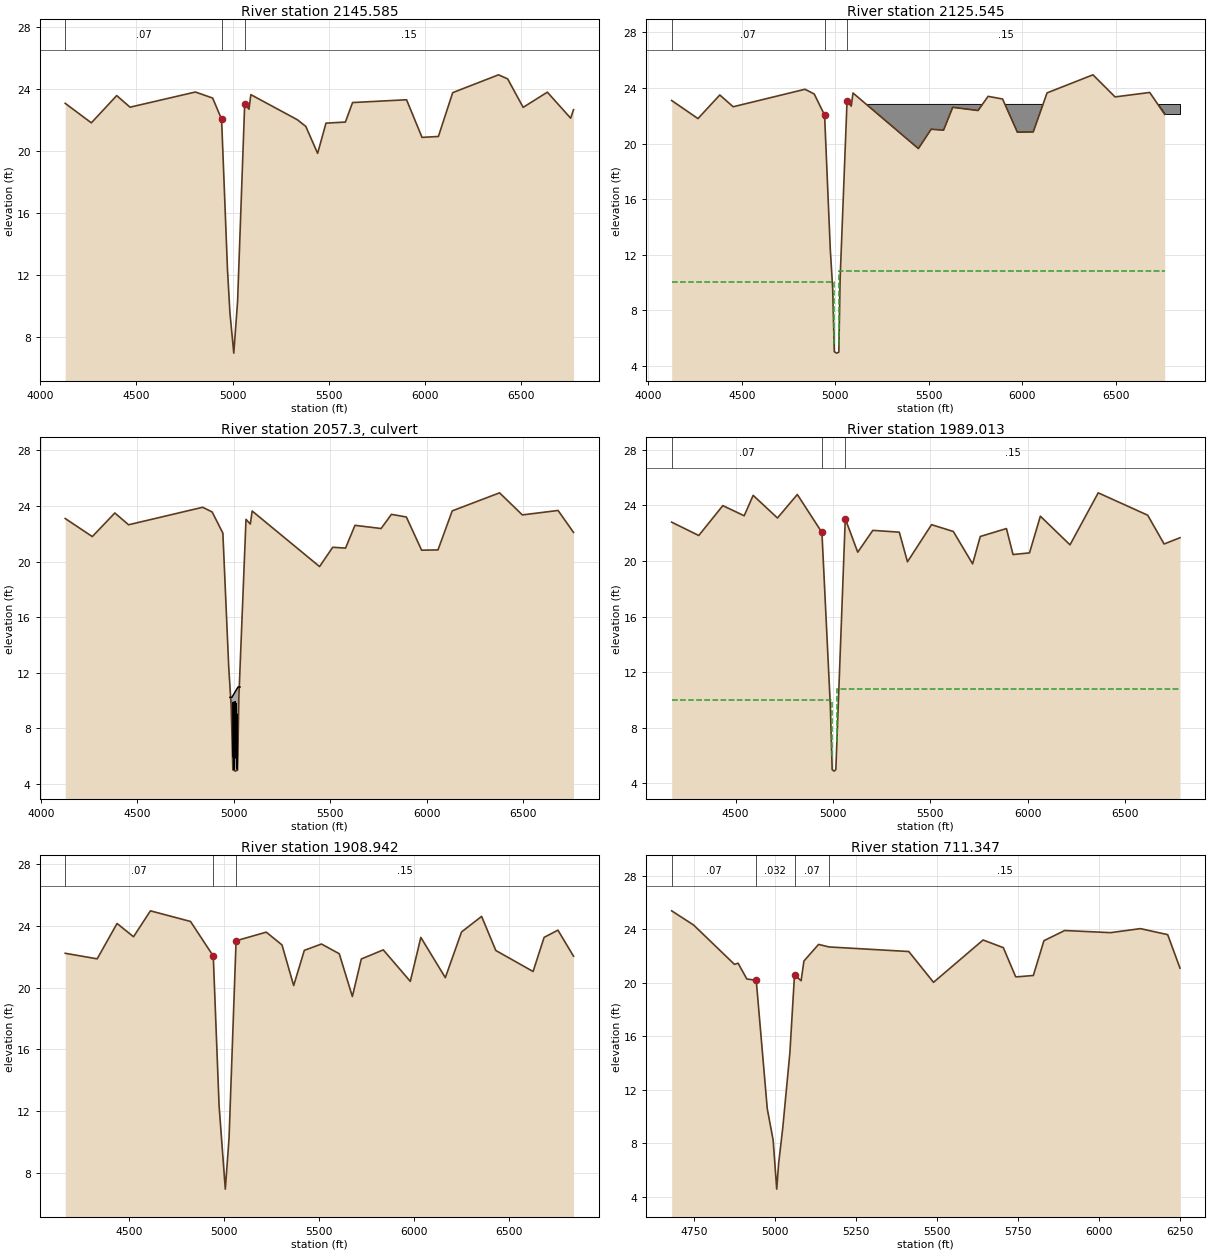
Type RM Length L Ch R = 1 ,2145.585,20.37,20.04,20.89
XS GIS Cut Line= 4
     3191545.391    13781999.425     3192139.619    13781396.021
     3192183.492    13781338.377     3193392.689    13780112.516
#Sta/Elev= 30
 4130.68   23.08 4266.48   21.82 4398.29   23.58 4467.51   22.83 4807.05   23.81
 4896.85   23.42 4943.27   22.05 4973.81   12.37 4986.54    9.56 5006.59    6.95
 5026.37   10.29 5063.25   23.04 5085.68    22.7 5095.25   23.64 5337.08   22.02
 5380.79   21.59 5442.22   19.85 5485.67    21.8 5586.54   21.87  5623.8   23.13
 5904.33   23.31 5984.75   20.88 6069.72   20.94 6144.12   23.77 6381.96   24.92
 6429.57   24.66 6510.19   22.82 6635.88    23.8 6756.99   22.12 6771.89   22.67
#Mann= 3 ,-1 , 0
 4130.68     .07       0 4943.27    .032       0 5063.25     .15       0
Bank Sta=4943.27,5063.25
XS Rating Curve= 0
Exp/Cntr=0.5,0.3

Type RM Length L Ch R = 1 ,2125.545,145.21,136.53,133.15
XS GIS Cut Line= 4
     3191559.641    13782013.459     3192154.762    13781409.147
     3192198.597    13781351.552     3193413.084     13780139.71
#Sta/Elev= 30
 4125.63    23.1 4266.27    21.8 4383.04    23.5 4454.29   22.65 4838.47   23.91
  4887.8   23.57 4943.27   22.05 4973.81   12.37 4986.54    9.56 4995.07    5.01
 5007.98    4.91 5019.34    4.98 5026.37   10.29 5063.25   23.04 5085.68    22.7
 5095.25   23.64 5444.72   19.64 5513.05   21.03 5579.46   20.97  5628.4   22.61
 5763.84   22.38 5817.46    23.4 5894.89   23.21 5974.05   20.82 6058.88   20.84
 6132.79   23.65 6378.18   24.95 6496.35   23.36 6681.68   23.68 6761.84    22.1
#Mann= 3 ,-1 , 0
 4125.63     .07       0 4943.27    .032       0 5063.25     .15       0
#XS Ineff= 2 , 0
       0    4994      10    5020       0    10.8
Permanent Ineff=
       F       F
#Block Obstruct= 1 ,-1
 5110.82 6843.55   22.82
Bank Sta=4943.27,5063.25
XS Rating Curve= 0
Exp/Cntr=0.5,0.3

Type RM Length L Ch R = 2 ,2057.3  ,,,
BEGIN DESCRIPTION:
unnamed road
END DESCRIPTION:
Bridge Culvert--1,0,-1,-1, 0
Deck Dist Width WeirC Skew NumUp NumDn MinLoCord MaxHiCord MaxSubmerge Is_Ogee
52,22,2.6,0, 4, 4, , , 0.95, 0, 0,0,,
    4980    4990    5022    5032
   10.22   10.22   10.97   10.97
                                
    4980    4990    5022    5032
   10.22   10.22   10.97   10.97
                                
Culvert=1,4,,30,0.012,0.5,1,1,3,5.9,4997,5.9,4997,Culvert #1  , 0 ,48
Culvert Bottom n=0.012
Culvert=1,4,,30,0.012,0.5,1,1,3,5,5002,5.7,5002,Culvert #2  , 0 ,48
Culvert Bottom n=0.012
Culvert=1,4,,30,0.012,0.5,1,1,3,5.94,5007,5.75,5007,Culvert #3  , 0 ,48
Culvert Bottom n=0.012
Culvert=1,4,,30,0.012,0.5,1,1,3,5.82,5012,4.97,5012,Culvert #4  , 0 ,48
Culvert Bottom n=0.012
Culvert=1,4,,30,0.012,0.5,1,1,3,5.03,5017,5.7,5017,Culvert #5  , 0 ,48
Culvert Bottom n=0.012
BC Design=,, 0 ,, 0 ,,,,,,
BC HTab HWMax=24.95

Type RM Length L Ch R = 1 ,1989.013,80.55,80.07,81.34
XS GIS Cut Line= 4
     3191745.208    13782099.105     3192250.151     13781512.37
     3192319.507    13781414.927     3193542.255    13780207.695
#Sta/Elev= 30
 4171.21   22.79 4310.39   21.83 4434.05   23.98 4543.82   23.25  4589.9   24.72
 4714.78   23.09 4816.84   24.78 4943.27   22.05 4986.54    9.56 4995.93    4.98
 5006.18    4.88 5014.72    4.99 5063.25   23.04 5127.23   20.63  5204.8    22.2
 5340.87   22.07  5382.8   19.94 5506.51   22.61 5618.47   22.12 5717.62   19.79
 5756.91   21.76 5891.38   22.33 5925.28   20.46 6009.92   20.58 6065.71   23.22
 6218.02   21.16    6363    24.9 6617.25   23.29 6701.57   21.22  6783.2   21.67
#Mann= 3 ,-1 , 0
 4171.21     .07       0 4943.27    .032       0 5063.25     .15       0
#XS Ineff= 2 , 0
       0    4994      10    5020       0    10.8
Permanent Ineff=
       F       F
Bank Sta=4943.27,5063.25
XS Rating Curve= 0
Exp/Cntr=0.5,0.3

Type RM Length L Ch R = 1 ,1908.942,1163.39,1197.59,1226.08
XS GIS Cut Line= 4
     3191805.845    13782151.289     3192313.191    13781561.761
     3192380.653    13781466.979     3193644.232    13780214.493
#Sta/Elev= 30
 4164.61   22.23 4332.72   21.87  4437.3   24.16 4523.87    23.3  4612.8   24.98
 4823.75   24.29 4943.27   22.05 4973.81   12.37 5006.59    6.95 5026.37   10.29
 5063.25   23.04 5221.96    23.6 5304.75   22.77 5366.11   20.14 5422.14   22.42
  5512.2   22.83 5605.85    22.2 5674.78   19.43 5721.84   21.86 5837.36   22.45
  5979.5   20.41 6034.88   23.26 6163.64   20.65 6248.83   23.61 6354.45   24.62
 6429.22   22.41 6625.16   21.05 6683.18   23.26 6755.77   23.73 6837.87   22.04
#Mann= 3 ,-1 , 0
 4164.61     .07       0 4943.27    .032       0 5063.25     .15       0
Bank Sta=4943.27,5063.25
XS Rating Curve= 0
Exp/Cntr=0.3,0.1

Type RM Length L Ch R = 1 ,711.347 ,772.82,711.35,763.86
XS GIS Cut Line= 4
     3192387.834    13782777.753     3192608.452    13782637.916
     3192706.349    13782571.853     3193722.145    13781952.539
#Sta/Elev= 30
 4679.92   25.38 4747.66   24.32 4873.81   21.38 4884.86   21.47 4911.85   20.29
 4940.95   20.19 4975.03   10.59 4993.15    8.25  5004.2    4.59 5010.11    6.52
 5022.86    9.18 5044.77   14.77 5059.05   20.59 5079.44   20.16 5088.13   21.63
  5133.3   22.87 5166.31   22.68 5411.85   22.34 5488.17   20.04 5641.13    23.2
 5703.65   22.63  5741.6   20.46 5746.62   20.45 5796.22   20.55 5828.96   23.15
 5893.09   23.91 6034.45   23.75  6126.9   24.05 6210.95    23.6 6248.93    21.1
#Mann= 4 ,-1 , 0
 4679.92     .07       0 4940.95    .032       0 5059.05     .07       0
 5166.31     .15       0
Bank Sta=4940.95,5059.05
XS Rating Curve= 0
Exp/Cntr=0.3,0.1

Chan Stop Cuts=-1

--- B104_05_00.g02 (geometry) ---

Geom Title=B104-05-00 June 2007 (Floodway)
Program Version=3.10

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
River Reach=B104-05-00      ,B104-05-00_0007